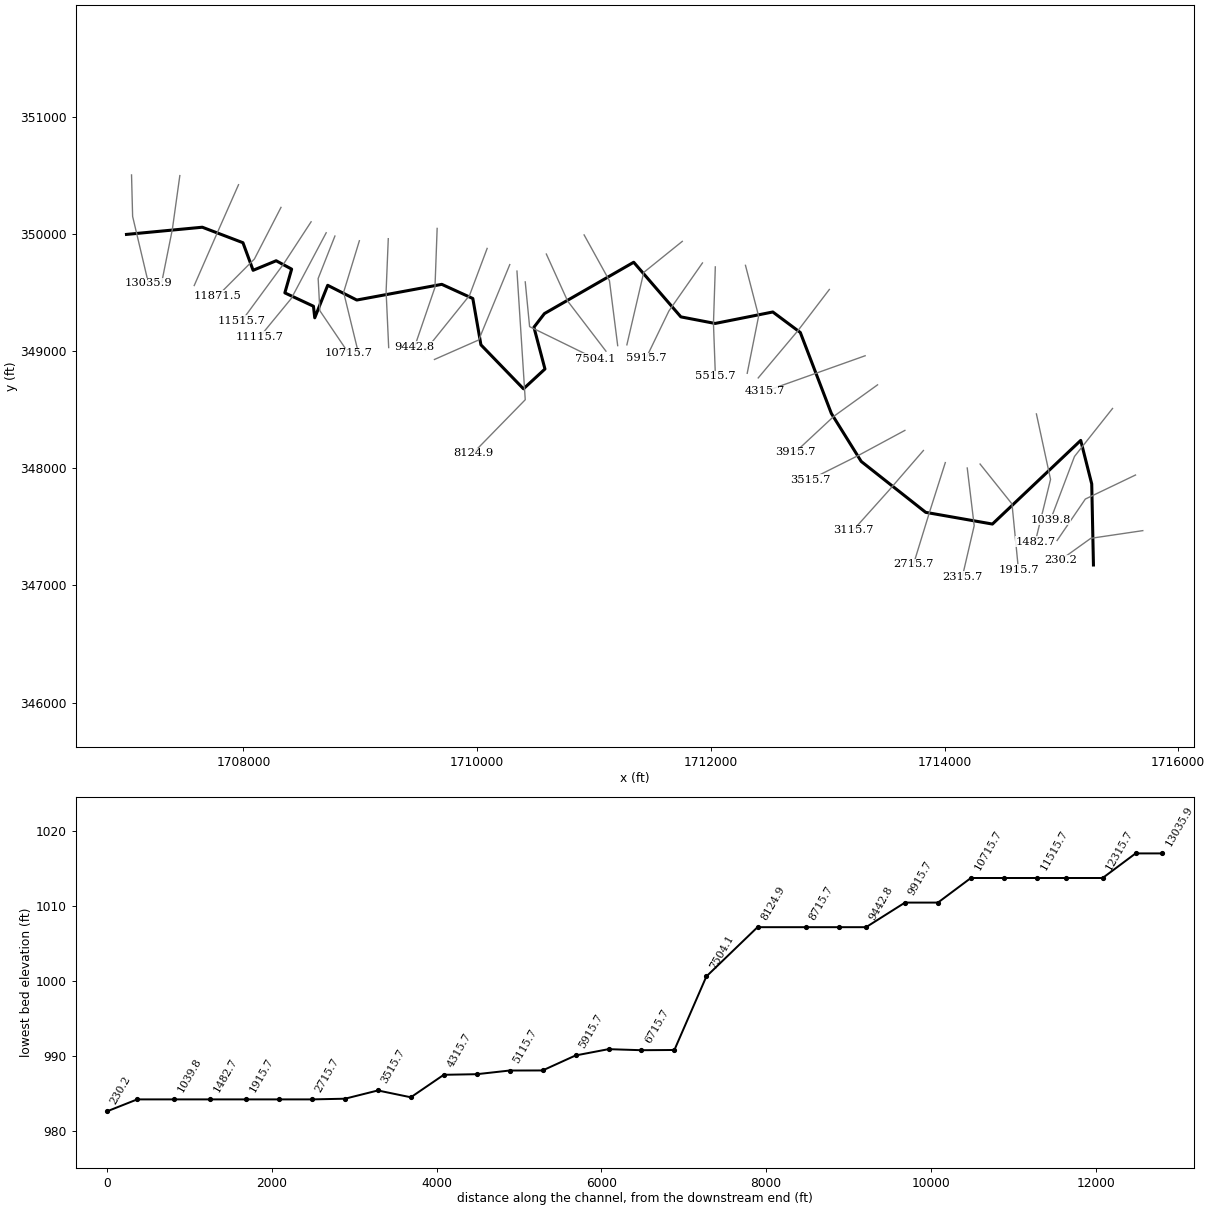
--- BngmnCrk2.prj (project) ---

Proj Title=BngmnCrk2
Current Plan=p01
Default Exp/Contr=0,0
English Units
Geom File=g01
Flow File=f01
Plan File=p01
BEGIN DESCRIPTION:
END DESCRIPTION:
DSS Export Rating Curves= 0
DSS Export Rating Curve Sorted= 0
DSS Export Volume Flow Curves= 0
DXF OffsetX= 0
DXF OffsetY= 0
DXF ScaleX= 0
DXF ScaleY= 0

--- BngmnCrk2.p01 (plan) ---

Plan Title=Floodplain
Program Version=4.00
Geom File=g01
Flow File=f01
K Sum by GR=0
Std Step Tol=0.01
Critical Tol=0.01
Num of Std Step Trials=20
Max Error Tol=0.3
Flow Tol Ratio=0.001
Split Flow NTrial=30
Split Flow Tol=0.02
Split Flow Ratio=0.02
Log Output Level=0
Friction Slope Method=1
Unsteady Friction Slope Method=2
Unsteady Bridges Friction Slope Method=1
Global Log Level=0
CheckData=False
Run HTab=0
Run UNet=0
Run PostProcess=0
UNET Theta=0
UNET Theta Warmup=0
UNET ZTol=0
UNET ZSATol=0
UNET MxIter=0
UNET MaxInSteps=0
UNET DtIC=0
UNET DtMin=0
UNET MaxCRTS=0
UNET WFStab=0
UNET SFStab=0
UNET WFX=0
UNET SFX=0
UNET DSS MLevel=0
UNET DZMax Abort=0
UNET Convert EG Bridges=0
UNET Use Existing IB Tables=0
UNET Froude Limit=0
UNET Froude Power=0
Write IC File=0
Echo Input=False
Echo Output=False
Write Detailed=0

--- BngmnCrk2.f01 (steady flow) ---

Flow Title=NFF Regression Equation
Program Version=4.00
Number of Profiles=1
Profile Names=P100yr
River Rch & RM=BngmnCrk2,Main      ,13035.9
2260.389
River Rch & RM=BngmnCrk2,Main      ,11115.7
2322.710
River Rch & RM=BngmnCrk2,Main      ,5115.7
2473.747
River Rch & RM=BngmnCrk2,Main      ,4715.7
3693.333
River Rch & RM=BngmnCrk2,Main      ,230.2
3733.938
Boundary for River Rch & Prof#=BngmnCrk2,Main      ,1
Up Type=0
Dn Type=3
Dn Slope=0.0008

--- BngmnCrk2.g01 (geometry) ---

Geom Title=USGS 3m DEM
Program Version=4.00

River Reach=BngmnCrk2       ,Main
Reach XY= 30
     1706998.692       349994.35     1707647.584      350055.759
     1707995.398      349923.595      1708082.37      349688.323
     1708279.731       349769.72     1708412.146      349698.372
      1708353.99      349495.813     1708598.862       349381.77
     1708609.938      349283.138     1708720.832       349560.29
     1708969.616      349434.699     1709697.272      349568.547
     1709962.686      349447.746     1710032.079      349052.631
     1710396.292      348677.289     1710580.055      348846.545
     1710485.691        349202.6     1710575.618      349319.137
      1711339.67      349757.012     1711743.226      349291.048
     1712036.431      349234.958     1712530.242      349332.738
     1712765.494      349157.925     1713030.967      348467.618
     1713286.732      348057.982     1713838.508      347623.714
     1714409.598      347523.914     1715165.278       348237.39
     1715259.497      347865.896     1715274.229      347174.718

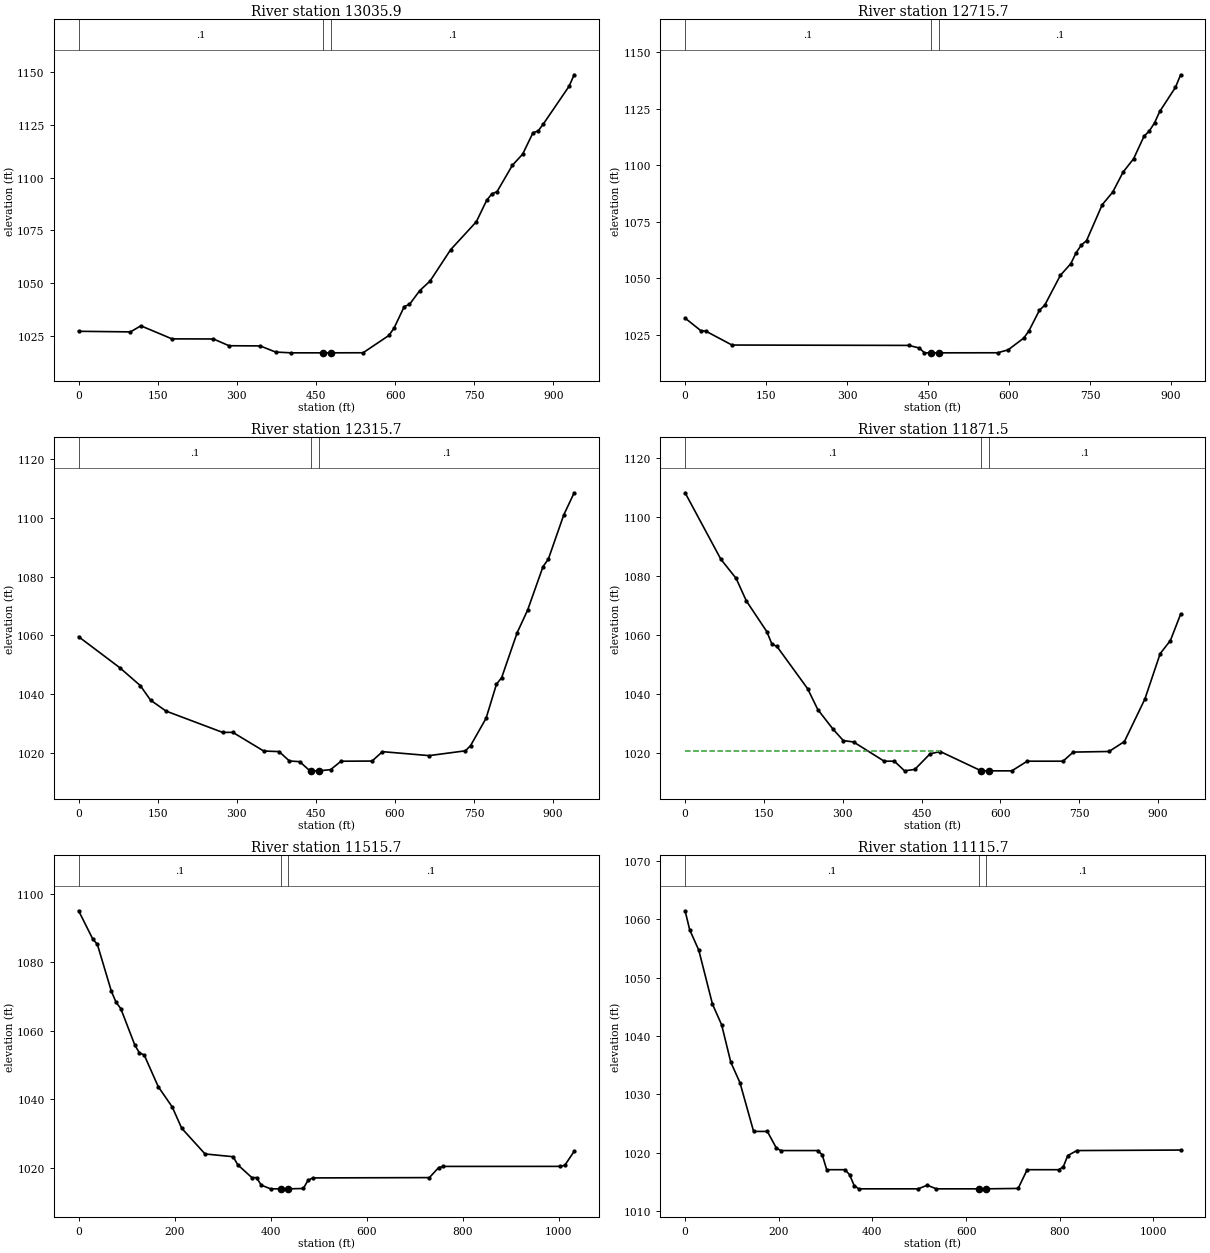
Type RM Length L Ch R = 1 ,13035.9 ,328.426,320.223,310.613
XS GIS Cut Line= 3
     1707041.952      350501.718      1707051.26      350148.021
      1707186.32      349578.433
#Sta/Elev= 30
       0 1027.25    98.3 1026.97   117.9 1029.85   176.9 1023.67   255.5 1023.62
     285 1020.42     344 1020.34   373.3 1017.44   402.6 1017.06   463.2 1017.06
   478.2 1017.06   539.2  1017.1     588 1025.28   597.7 1028.71   617.2 1038.97
     627 1039.95   646.5 1046.49     666    1051     705 1065.84   753.8 1079.08
   773.3 1089.18   783.1 1092.26   792.9 1093.28   822.1 1105.79   841.6 1111.07
   861.2 1121.21   870.9 1122.03   880.7  1125.3   929.4 1143.11   939.2  1148.6
#Mann= 3 , 0 , 0
       0      .1       0   463.2    .045       0   478.2      .1       0
Bank Sta=463.2,478.2
XS Rating Curve= 0 ,0
Exp/Cntr=0.3,0.1

Type RM Length L Ch R = 1 ,12715.7 ,406.466,400,395.024
XS GIS Cut Line= 3
     1707455.273      350496.055     1707391.256      350037.803
     1707301.518      349591.492
#Sta/Elev= 30
       0  1032.4    28.9  1026.9    38.6 1026.62    86.8 1020.51   414.5 1020.34
   433.8 1019.19   443.4 1017.06   455.2 1017.06   470.2 1017.06   578.9 1017.09
   598.3 1018.37   627.4 1023.59   637.1 1026.87   656.4 1035.89   666.1 1038.09
   695.2 1051.33   714.5 1056.46   724.2 1061.26   733.9 1064.66   743.6 1066.63
   772.7 1082.53     792 1088.04   811.4 1096.94   830.8 1102.82   850.1 1112.76
   859.8 1115.06   869.5 1118.64   879.2 1123.69   908.3 1134.37   917.9 1139.91
#Mann= 3 , 0 , 0
       0      .1       0   455.2    .045       0   470.2      .1       0
Bank Sta=455.2,470.2
XS Rating Curve= 0 ,0
Exp/Cntr=0.3,0.1

Type RM Length L Ch R = 1 ,12315.7 ,452.646,444.226,435.723
XS GIS Cut Line= 3
      1707957.62       350418.45     1707775.883      350008.342
     1707578.407      349558.338
#Sta/Elev= 30
       0 1059.52      78 1048.96     117 1042.84   136.5 1037.87   165.8 1034.16
     273  1026.9   292.5  1026.9   351.1 1020.54   380.3 1020.34   399.8 1017.14
   419.3 1016.91   438.8 1013.78   441.1 1013.78   456.1 1013.78   478.1  1014.2
   497.7 1017.06   556.7 1017.12   576.3 1020.32   664.8 1018.97   733.6 1020.61
   743.4 1022.35   772.9 1031.71   792.6 1043.32   802.4 1045.54   831.9 1060.91
   851.5 1068.51     881 1083.46   890.9 1085.93   920.3 1101.08     940  1108.6
#Mann= 3 , 0 , 0
       0      .1       0   441.1    .045       0   456.1      .1       0
Bank Sta=441.1,456.1
XS Rating Curve= 0 ,0
Exp/Cntr=0.3,0.1

Type RM Length L Ch R = 1 ,11871.5 ,350.509,355.774,359.797
XS GIS Cut Line= 3
     1708321.096      350224.986     1708093.736      349785.016
      1707777.27      349468.551
#Sta/Elev= 30
       0 1108.27      68  1085.7    97.1 1079.17   116.5 1071.53   155.4 1061.11
   165.1 1056.89   174.8 1056.04   233.1  1041.7   252.5  1034.6   281.6 1027.91
     301 1024.07   320.5 1023.59   378.7 1017.06   398.1 1017.06   417.6 1013.78
     437 1014.26   466.1 1019.56   485.5 1020.34   563.3 1013.78   578.3 1013.78
   621.7 1013.78   650.9 1017.06     719 1017.06   738.5 1020.15   806.6 1020.36
   835.8 1023.73   874.7 1038.15   903.9 1053.62   923.3 1058.06   942.8 1067.03
#Mann= 3 , 0 , 0
       0      .1       0   563.3    .045       0   578.3      .1       0
#XS Ineff= 2 , 0
          485.56 1020.39
Permanent Ineff=
       F       F
Bank Sta=563.3,578.3
XS Rating Curve= 0 ,0
Exp/Cntr=0.3,0.1

Type RM Length L Ch R = 1 ,11515.7 ,397.521,400,399.047
XS GIS Cut Line= 3
      1708578.72      350101.971     1708343.756      349743.157
     1707986.167      349257.756
#Sta/Elev= 30
       0    1095    29.2 1086.81      39 1085.18    68.2 1071.48      78 1068.25
    87.7 1066.45     117 1055.78   126.7 1053.45   136.5 1052.89   165.7 1043.64
     195 1037.67   214.5  1031.5   263.2 1023.97   321.7 1023.16   331.4  1020.8
   360.7 1017.06   370.4 1017.06   380.2 1014.87   399.7 1013.78   421.4 1013.78
   436.4 1013.78   467.8 1013.88   477.5 1016.23   487.2 1016.97   730.3 1017.06
   749.8 1020.01   759.5 1020.33  1002.6 1020.34  1012.3 1020.66  1031.8 1024.75
#Mann= 3 , 0 , 0
       0      .1       0   421.4    .045       0   436.4      .1       0
Bank Sta=421.4,436.4
XS Rating Curve= 0 ,0
Exp/Cntr=0.3,0.1

Type RM Length L Ch R = 1 ,11115.7 ,393.282,400,425.896
XS GIS Cut Line= 3
     1708707.891      350008.468     1708409.784      349448.767
     1708139.977      349121.663
#Sta/Elev= 30
       0 1061.44     9.8 1058.18    29.3 1054.67    58.5 1045.42      78  1041.9
    97.6 1035.48   117.1 1031.99   146.3 1023.62   175.6 1023.62   195.1 1020.74
   204.9 1020.34   282.9 1020.34   292.7 1019.64   302.4 1017.06   341.5 1017.06
   351.2 1016.21     361 1014.35   370.7 1013.78   497.6 1013.78   517.1  1014.4
   536.6 1013.78   626.6 1013.78   641.6 1013.78   711.2 1013.85   730.5 1017.06
     798 1017.06   807.6 1017.56   817.2 1019.48   836.5 1020.34  1058.2 1020.43
#Mann= 3 , 0 , 0
       0      .1       0   626.6    .045       0   641.6      .1       0
Bank Sta=626.6,641.6
XS Rating Curve= 0 ,0
Exp/Cntr=0.3,0.1

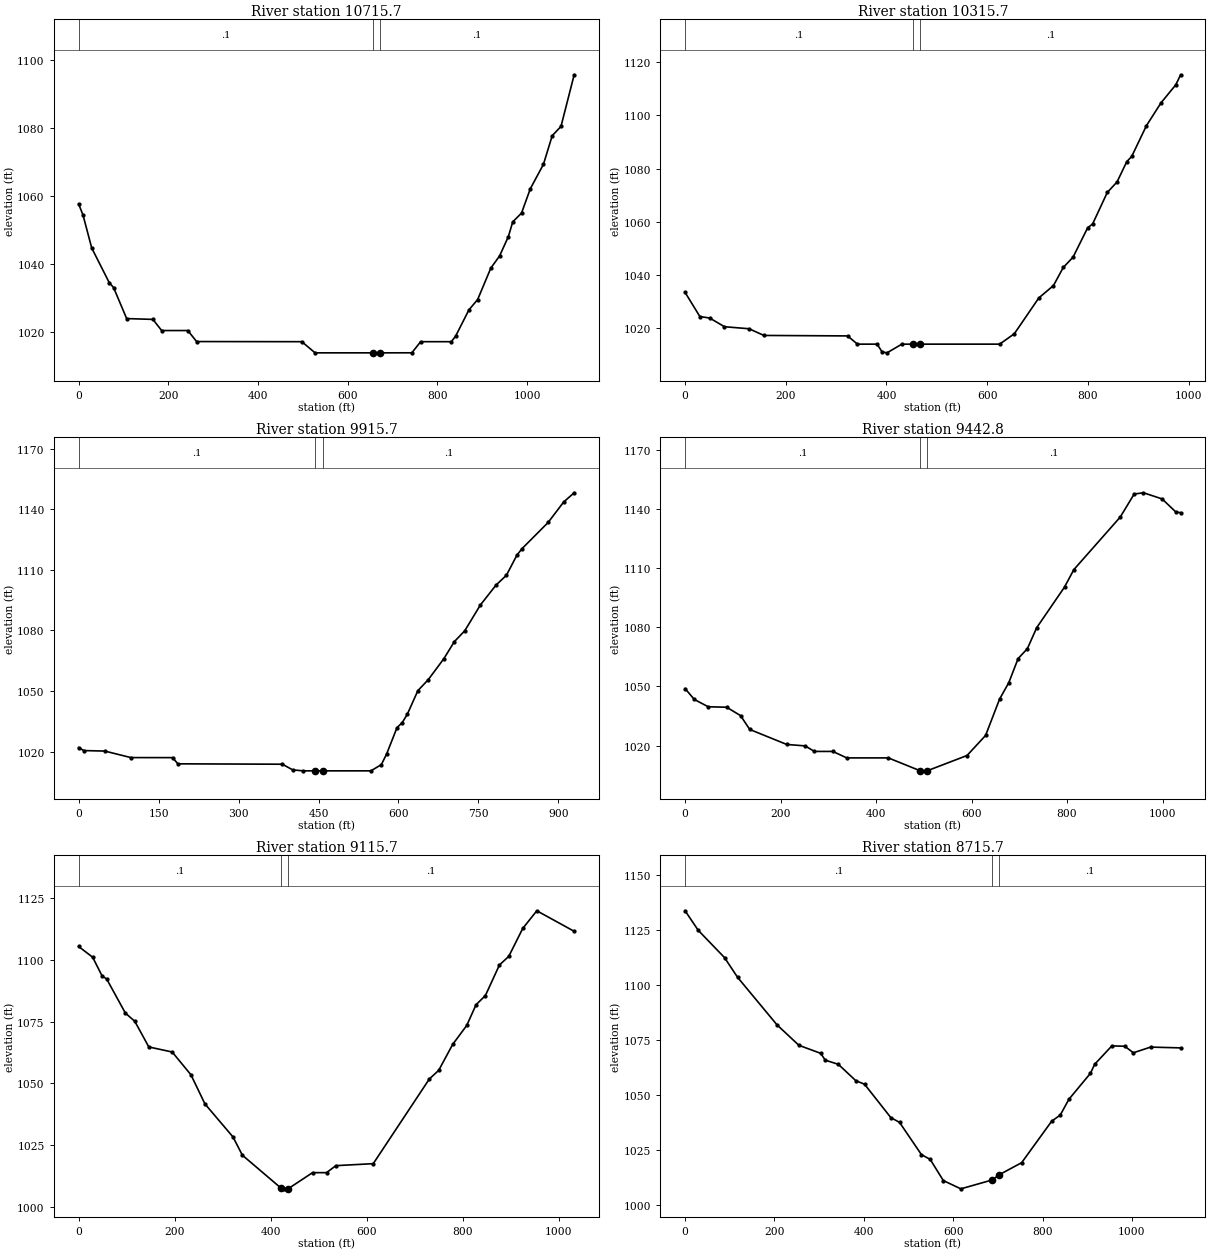
Type RM Length L Ch R = 1 ,10715.7 ,393.217,400,402.536
XS GIS Cut Line= 4
     1708782.514      349980.481     1708639.025      349618.264
     1708653.727      349343.471     1708900.799       348979.31
#Sta/Elev= 30
       0 1057.57     9.7 1054.36    29.2 1044.62    68.2 1034.45    77.9 1032.99
   107.1 1023.86   165.6 1023.62   185.1 1020.34   243.5 1020.34     263  1017.1
   497.7 1017.06   527.2 1013.78   657.3 1013.78   672.3 1013.78     743 1013.79
   762.6 1017.06     831 1017.06   840.8 1018.75   870.2 1026.42   889.7 1029.47
     919  1038.7   938.6  1042.3   958.2 1047.99   967.9 1052.31   987.5  1054.9
  1007.1 1062.06  1036.4 1069.26    1056 1077.69  1075.5  1080.4  1104.9  1095.6
#Mann= 3 , 0 , 0
       0      .1       0   657.3    .045       0   672.3      .1       0
Bank Sta=657.3,672.3
XS Rating Curve= 0 ,0
Exp/Cntr=0.3,0.1

Type RM Length L Ch R = 1 ,10315.7 ,394.755,400,384.394
XS GIS Cut Line= 3
     1708991.852      349940.357     1708856.982      349500.919
     1708981.512      348991.412
#Sta/Elev= 30
       0 1033.28    29.3  1024.2    48.9 1023.62    78.2 1020.35   127.1 1019.58
   156.5 1017.06   322.7 1016.88   342.3 1013.78   381.4 1013.78   391.2 1010.86
     401  1010.5   430.3 1013.76   452.2 1013.78   467.2 1013.78   624.8 1013.78
   653.9  1017.7   702.5  1031.2   731.6 1035.87   751.1 1042.69   770.5 1046.57
   799.6 1057.69   809.3 1059.07   838.5 1070.97   857.9 1074.94   877.3 1082.63
     887 1084.54   916.2 1096.14   945.3 1104.79   974.5 1111.56   984.2 1115.35
#Mann= 3 , 0 , 0
       0      .1       0   452.2    .045       0   467.2      .1       0
Bank Sta=452.2,467.2
XS Rating Curve= 0 ,0
Exp/Cntr=0.3,0.1

Type RM Length L Ch R = 1 ,9915.7  ,472.461,472.934,452.663
XS GIS Cut Line= 3
     1709239.201       349957.91     1709220.622      349507.641
     1709242.701      349029.206
#Sta/Elev= 30
       0 1022.01     9.8 1020.53      49 1020.29      98 1017.06   176.3 1017.04
   186.1 1013.97   382.1 1013.78   401.7 1010.96   421.3  1010.5   443.2  1010.5
   458.2  1010.5   548.4  1010.5   567.9 1013.59   577.7  1018.8   597.3 1031.91
     607 1034.34   616.8 1038.64   636.4  1050.2   655.9 1055.65   685.2 1066.04
   704.8 1074.46   724.3 1079.82   753.7 1092.62     783 1102.46   802.5 1107.31
   822.1 1117.24   831.9 1120.53   880.7 1133.45     910 1143.63   929.6 1148.16
#Mann= 3 , 0 , 0
       0      .1       0   443.2    .045       0   458.2      .1       0
Bank Sta=443.2,458.2
XS Rating Curve= 0 ,0
Exp/Cntr=0.3,0.1

Type RM Length L Ch R = 1 ,9442.8  ,332.249,327.066,328.589
XS GIS Cut Line= 3
     1709657.449      350045.635     1709638.834      349543.013
     1709464.929      349037.175
#Sta/Elev= 30
       0 1048.91    19.3 1043.41    48.4 1039.71    87.1 1039.46   116.1 1035.22
   135.4  1028.2   212.8  1020.6   251.5 1019.86   270.8 1017.06   309.5 1017.06
   338.5 1013.78   425.6 1013.78   491.7 1007.32   493.3 1007.22   506.7 1007.22
   590.5 1014.99   629.4 1025.17   658.6 1043.54     678 1051.93   697.5 1064.13
   716.9 1069.16   736.4 1079.78   794.7 1100.39   814.2 1109.22   911.4 1135.87
   940.6 1147.55   960.1 1148.18     999 1145.08  1028.1 1138.38  1037.9 1138.09
#Mann= 3 , 0 , 0
       0      .1       0   491.7    .045       0   506.7      .1       0
Bank Sta=491.7,506.7
XS Rating Curve= 0 ,0
Exp/Cntr=0.3,0.1

Type RM Length L Ch R = 1 ,9115.7  ,394.883,400,389.119
XS GIS Cut Line= 3
     1710085.329      349874.896     1709934.361      349473.786
     1709555.641      349004.352
#Sta/Elev= 30
       0 1105.47    29.2 1101.12    48.7 1093.59    58.4 1092.29    97.4 1078.45
   116.9 1075.15   146.1 1064.75   194.8 1062.69   233.8 1053.47     263 1041.64
   321.4 1028.25   340.9 1020.86   421.1 1007.56   428.6 1007.22   436.1 1007.24
     487 1013.78   516.1 1013.78   535.6 1016.62   613.4 1017.43   730.2 1051.77
   749.6 1055.24   778.8 1065.79     808 1073.45   827.4 1081.85   846.9 1085.59
   876.1 1097.98   895.5 1101.46   924.7 1112.81   953.9 1119.95  1031.7 1111.63
#Mann= 3 , 0 , 0
       0      .1       0   421.1    .045       0   436.1      .1       0
Bank Sta=421.1,436.1
XS Rating Curve= 0 ,0
Exp/Cntr=0.3,0.1

Type RM Length L Ch R = 1 ,8715.7  ,586.77,590.784,618.343
XS GIS Cut Line= 3
     1710278.985      349736.833     1710013.232      349094.063
     1709634.463       348927.81
#Sta/Elev= 30
       0 1133.87    29.4 1124.97    88.2 1112.55   117.6 1103.52   205.7 1081.92
   254.7  1072.6   303.7 1068.93   313.5 1065.86   342.9 1063.94   382.1 1056.49
   401.7 1054.87   460.4 1039.69     480 1037.49     529 1022.81   548.6 1020.63
     578 1010.99   617.2 1007.22     688  1011.3     703 1013.63   753.3 1019.13
   820.6 1038.04   839.8 1040.83   859.1 1048.02   907.2 1059.81   916.8 1063.96
   955.3 1072.34   984.1 1072.16  1003.4 1069.19  1041.9 1071.78  1109.2 1071.42
#Mann= 3 , 0 , 0
       0      .1       0     688    .045       0     703      .1       0
Bank Sta=688,703
XS Rating Curve= 0 ,0
Exp/Cntr=0.3,0.1

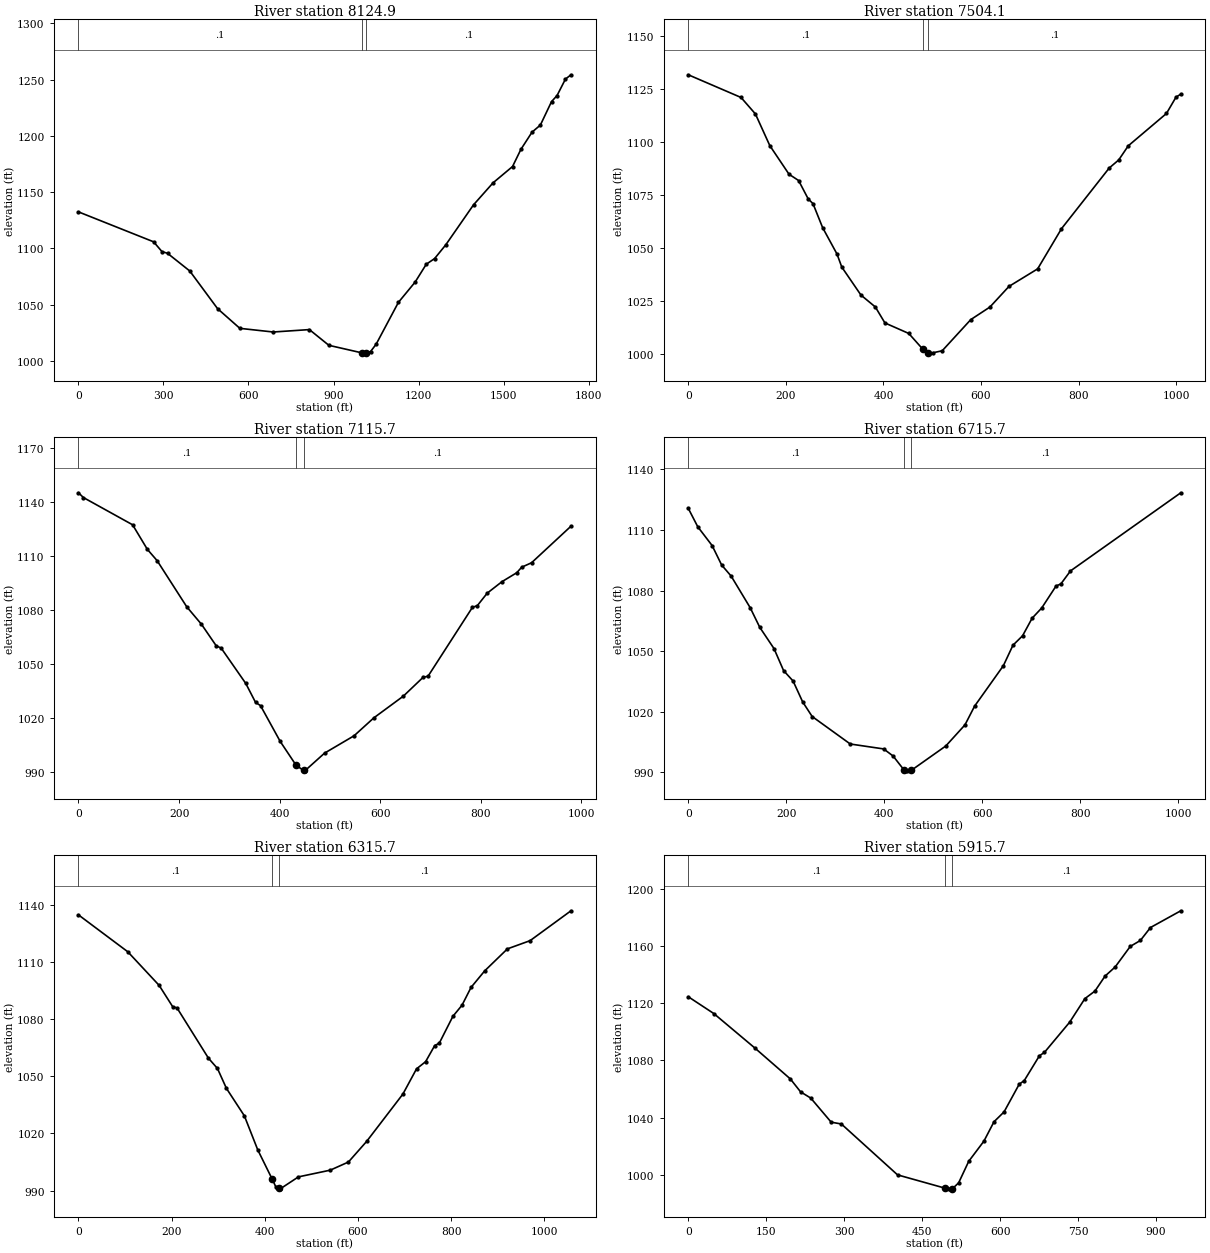
Type RM Length L Ch R = 1 ,8124.9  ,598.241,620.824,643.309
XS GIS Cut Line= 3
     1710340.464      349681.697     1710411.383      348584.308
     1709964.607      348128.225
#Sta/Elev= 30
       0 1132.46   265.1 1105.87   294.6 1097.18   314.2 1095.67   392.7 1079.96
   490.9 1046.47   569.5 1028.98   687.3 1025.73   814.9 1027.88   883.7  1013.9
   999.2 1007.25  1001.5 1007.22  1014.2 1007.22  1030.9  1008.4  1050.6 1014.95
  1129.1 1052.08  1188.1  1070.1  1227.4 1085.95  1256.8 1090.98  1296.1 1103.15
  1394.3 1138.78  1463.1 1158.28  1531.9 1172.78  1561.3 1187.99  1600.6 1203.29
  1630.1 1209.61  1669.4 1230.41    1689 1235.86  1718.5 1250.43  1738.1 1254.28
#Mann= 3 , 0 , 0
       0      .1       0   999.2    .045       0  1014.2      .1       0
Bank Sta=999.2,1014.2
XS Rating Curve= 0 ,0
Exp/Cntr=0.3,0.1

Type RM Length L Ch R = 1 ,7504.1  ,403.724,388.393,378.369
XS GIS Cut Line= 3
     1710411.383      349589.552     1710448.614      349207.932
     1711011.311      348933.801
#Sta/Elev= 30
       0 1131.89   108.1 1121.18   137.6  1113.4   167.1 1098.45   206.5 1084.94
   226.1 1081.98   245.8 1073.29   255.6 1071.07   275.3 1059.76   304.8 1047.28
   314.6 1041.13   353.9 1027.91   383.4 1022.29     403 1014.76   451.9  1009.8
   481.2 1002.23     491 1000.78   500.8 1000.65   520.4 1001.62     579 1016.34
   618.2 1022.26   657.3 1032.01     716 1040.28   764.9 1059.24   862.7 1087.88
   882.2  1091.7   901.8 1098.37     980 1113.62   999.6 1121.34  1009.4 1122.75
#Mann= 3 , 0 , 0
       0      .1       0   481.2    .045       0     491      .1       0
Bank Sta=481.2,491
XS Rating Curve= 0 ,0
Exp/Cntr=0.3,0.1

Type RM Length L Ch R = 1 ,7115.7  ,398.124,400,387.999
XS GIS Cut Line= 3
     1710591.837      349826.961      1710774.01      349426.251
     1711102.023      348998.548
#Sta/Elev= 30
       0 1145.28     9.8 1142.63   107.6  1127.5   136.9 1113.87   156.5 1107.53
   215.2 1081.97   244.5 1072.25   273.9 1060.27   283.7 1059.01   332.6 1039.39
   352.1 1028.83   361.9 1027.07     401 1007.21   432.7  993.92   447.7  991.03
     450  990.84   489.2 1000.66     548 1010.33   587.2 1020.26     646 1032.35
   685.2 1042.79     695 1043.39   783.2 1081.63     793  1082.6   812.6 1089.51
     842 1095.91   871.4 1100.88   881.2 1103.95   900.8 1106.41   979.2 1126.72
#Mann= 3 , 0 , 0
       0      .1       0   432.7    .045       0   447.7      .1       0
Bank Sta=432.7,447.7
XS Rating Curve= 0 ,0
Exp/Cntr=0.3,0.1

Type RM Length L Ch R = 1 ,6715.7  ,431.513,400,394.787
XS GIS Cut Line= 3
     1710915.147       349990.14     1711132.126      349598.977
     1711202.528      349045.697
#Sta/Elev= 30
       0 1120.66    19.4 1111.54    48.6 1102.29    68.1 1092.64    87.5 1087.15
   126.4 1071.49   145.9 1061.81     175 1051.27   194.5  1040.4   213.9 1035.24
   233.4 1024.93   252.8 1017.69   330.6 1004.08   398.7 1001.65   418.1  998.12
   439.8  991.38   447.3  990.81   454.8  990.99   525.6 1003.12   564.7 1013.56
   584.3 1022.82     643 1042.82   662.6 1052.96   682.2 1057.63   701.7 1066.32
   721.3 1071.39   750.6 1082.27   760.4  1083.3     780 1089.72  1005.1 1128.38
#Mann= 3 , 0 , 0
       0      .1       0   439.8    .045       0   454.8      .1       0
Bank Sta=439.8,454.8
XS Rating Curve= 0 ,0
Exp/Cntr=0.3,0.1

Type RM Length L Ch R = 1 ,6315.7  ,393.565,400,392.432
XS GIS Cut Line= 3
     1711755.406      349935.157     1711425.295      349669.972
     1711281.213      349052.687
#Sta/Elev= 30
       0 1134.71   105.9 1115.35   173.2 1097.71   202.1 1086.59   211.7 1085.83
   279.1 1059.48   298.3 1054.14   317.6 1043.68   356.1 1029.27   384.9 1011.38
   415.9  996.01   423.4  992.12   430.9  991.22   433.2  990.95   472.2  997.23
   540.5 1000.75   579.5 1005.02   618.5 1015.81   696.5  1040.7   725.7 1053.91
   745.2 1057.68   764.8 1066.17   774.5 1067.36   803.8 1081.49   823.3 1087.29
   842.8 1096.68     872 1105.32   920.8 1116.88   969.5 1121.19  1057.3 1136.87
#Mann= 3 , 0 , 0
       0      .1       0   415.9    .045       0   430.9      .1       0
Bank Sta=415.9,430.9
XS Rating Curve= 0 ,0
Exp/Cntr=0.3,0.1

Type RM Length L Ch R = 1 ,5915.7  ,386.925,400,411.019
XS GIS Cut Line= 3
     1711928.045      349750.966      1711640.52      349340.849
     1711445.535      348938.722
#Sta/Elev= 30
       0 1124.48    49.1 1112.74   127.7 1088.75   196.4    1067   216.1 1057.96
   235.7  1053.6     275 1036.74   294.6 1035.48   402.7  999.88   493.4  990.65
   500.9  990.11   508.4  990.23   520.3  994.31   539.7 1009.37   568.9 1023.46
   588.3 1037.02   607.7 1043.93   636.9 1063.33   646.6 1065.85   675.7 1083.17
   685.5 1085.61     734 1106.71   763.2 1123.16   782.6 1128.46     802 1138.91
   821.5 1145.31   850.6  1159.7     870 1163.84   889.5 1172.91   947.8 1184.62
#Mann= 3 , 0 , 0
       0      .1       0   493.4    .045       0   508.4      .1       0
Bank Sta=493.4,508.4
XS Rating Curve= 0 ,0
Exp/Cntr=0.3,0.1

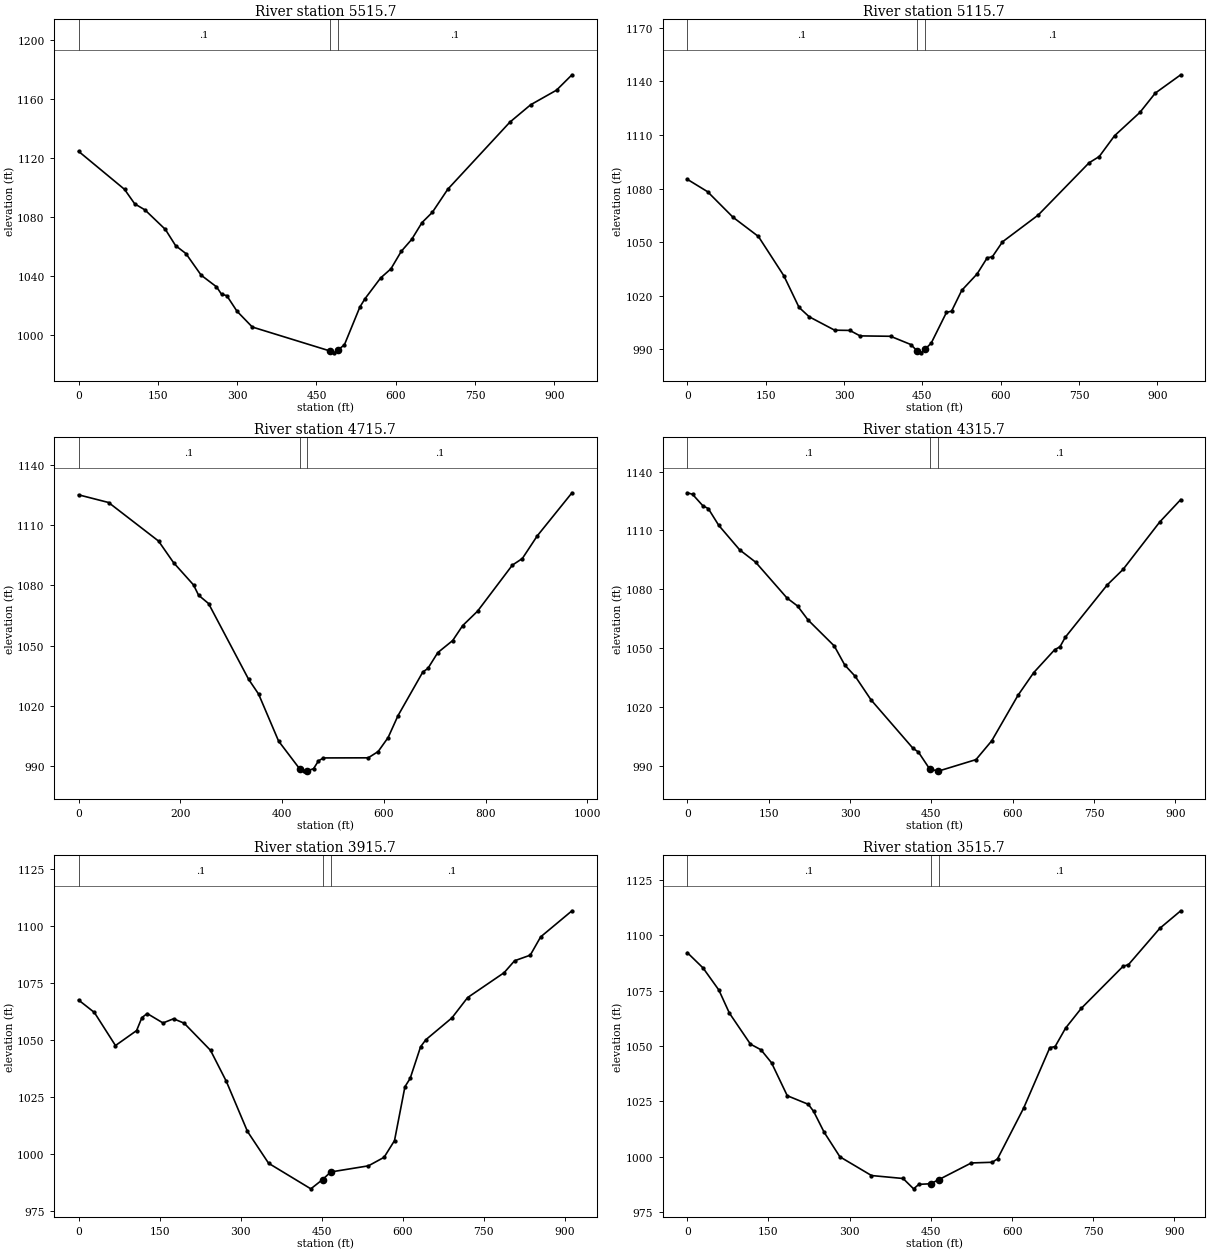
Type RM Length L Ch R = 1 ,5515.7  ,393.59,400,393.91
XS GIS Cut Line= 3
     1712038.062       349717.39     1712022.187       349234.43
     1712038.845      348784.719
#Sta/Elev= 30
       0 1124.55      87 1098.78   106.3 1088.95   125.6 1084.88   164.3 1071.62
   183.6 1060.66     203 1055.35   231.9 1040.68   260.9  1032.8   270.6  1027.7
   280.3 1026.86   299.6 1016.32   328.6 1005.59   475.7  989.35   483.2  988.11
   490.7  990.09   502.8  993.53   532.1 1019.16   541.9 1024.82   571.3  1038.8
   590.8 1044.99   610.4 1056.86     630 1064.88   649.5 1076.26   669.1 1083.23
   698.4 1098.91   815.8  1144.3     855 1156.03   903.9 1165.92   933.2 1176.34
#Mann= 3 , 0 , 0
       0      .1       0   475.7    .045       0   490.7      .1       0
Bank Sta=475.7,490.7
XS Rating Curve= 0 ,0
Exp/Cntr=0.3,0.1

Type RM Length L Ch R = 1 ,5115.7  ,423.744,400,382.138
XS GIS Cut Line= 3
     1712296.131      349730.641     1712408.708      349297.485
     1712311.025      348809.938
#Sta/Elev= 30
       0 1085.25    38.9  1078.3    87.6    1064   136.2 1053.24   184.9 1031.25
     214 1013.54   233.5 1008.28   282.1 1000.79   311.3 1000.65   330.8  997.59
   389.2  997.37   428.1  992.74     440  989.17   447.5   988.1     455  990.05
     467  993.51   496.3 1010.76     506 1011.42   525.5 1023.07   554.8 1032.24
   574.3 1041.32     584 1041.85   603.5 1050.23   671.8 1065.21   769.3 1094.48
   788.8    1098     818 1109.61   866.8 1122.75     896 1133.49   944.8 1143.76
#Mann= 3 , 0 , 0
       0      .1       0     440    .045       0     455      .1       0
Bank Sta=440,455
XS Rating Curve= 0 ,0
Exp/Cntr=0.3,0.1

Type RM Length L Ch R = 1 ,4715.7  ,413.048,400,388.01
XS GIS Cut Line= 3
     1713013.887      349524.699     1712745.074      349173.557
     1712405.164      348770.298
#Sta/Elev= 30
       0 1125.04      59 1121.21   157.2 1102.02   186.7 1091.27     226 1080.16
   235.9 1075.05   255.5  1070.9   334.1 1033.23   353.8 1025.83   393.1 1002.43
   434.7  988.54   442.2  987.61   449.7  987.61   461.8  988.69   471.5  992.58
   481.3  994.04   569.2  994.09   588.7  997.21   608.3 1004.18   627.8 1015.12
   676.6 1036.86   686.4 1038.57   705.9 1046.47   735.2 1052.49   754.8 1059.92
   784.1 1067.12   852.4 1090.03     872 1093.31   901.3 1104.58   969.6 1126.05
#Mann= 3 , 0 , 0
       0      .1       0   434.7    .045       0   449.7      .1       0
Bank Sta=434.7,449.7
XS Rating Curve= 0 ,0
Exp/Cntr=0.3,0.1

Type RM Length L Ch R = 1 ,4315.7  ,393.6,400,409.24
XS GIS Cut Line= 3
     1713320.292      348959.367     1712891.471      348807.256
      1712462.65      348655.145
#Sta/Elev= 30
       0 1129.21     9.7 1128.43      29 1122.51    38.7 1121.18    58.1 1112.59
    96.8 1100.08   125.9 1093.89   183.9 1075.59   203.3 1071.54   222.7 1064.41
   271.1 1051.15   290.4 1041.45   309.8 1035.65   338.8 1023.71   416.3  998.99
     426  997.18   447.5  988.27   462.5  987.55   464.7  987.53   532.4  993.25
   561.5 1002.85   609.9 1026.03   638.9 1037.59   677.7  1049.3   687.3 1050.74
     697 1055.56   774.5 1082.28   803.5 1090.12   871.3 1114.34     910 1125.75
#Mann= 3 , 0 , 0
       0      .1       0   447.5    .045       0   462.5      .1       0
Bank Sta=447.5,462.5
XS Rating Curve= 0 ,0
Exp/Cntr=0.3,0.1

Type RM Length L Ch R = 1 ,3915.7  ,402.911,400,393.572
XS GIS Cut Line= 3
      1713426.49      348711.411     1713053.239      348443.611
     1712720.242      348134.685
#Sta/Elev= 30
       0 1067.54    29.3 1062.06    68.4 1047.51   107.5 1054.09   117.3 1059.78
   127.1 1061.59   156.4 1057.44   175.9 1059.28   195.5 1057.35   244.4  1045.4
   273.7 1031.74   312.8 1009.75   351.9  995.77   430.1  984.53   451.9  988.62
   466.9  991.94   536.7  994.64   565.7  998.39     585 1005.73   604.3 1029.41
     614 1033.08   633.3 1046.98     643 1050.07   691.3 1059.67   720.3 1068.59
     788 1079.55   807.3 1084.78   836.3 1087.24   855.6 1095.28   913.6 1106.75
#Mann= 3 , 0 , 0
       0      .1       0   451.9    .045       0   466.9      .1       0
Bank Sta=451.9,466.9
XS Rating Curve= 0 ,0
Exp/Cntr=0.3,0.1

Type RM Length L Ch R = 1 ,3515.7  ,391.824,400,408.448
XS GIS Cut Line= 3
      1713660.53      348322.841     1713257.907       348106.65
     1712851.059      347903.723
#Sta/Elev= 30
       0 1092.13    29.2 1085.18    58.3 1075.24    77.8 1064.81   116.7 1050.79
   136.1 1048.25   155.6 1042.39   184.7  1027.5   223.6 1023.62   233.4 1020.43
   252.8 1011.01     282   999.9   340.3  991.45   398.7  990.11   418.1  985.44
   427.8  987.46   449.5  987.74   464.5  989.58   524.7  997.13   563.4  997.44
   573.1  998.98   621.4 1021.91   669.8 1049.23   679.5 1049.68   698.8 1058.01
   727.8 1066.94   805.2 1085.97   814.9 1086.66   872.9 1103.09   911.6 1111.02
#Mann= 3 , 0 , 0
       0      .1       0   449.5    .045       0   464.5      .1       0
Bank Sta=449.5,464.5
XS Rating Curve= 0 ,0
Exp/Cntr=0.3,0.1

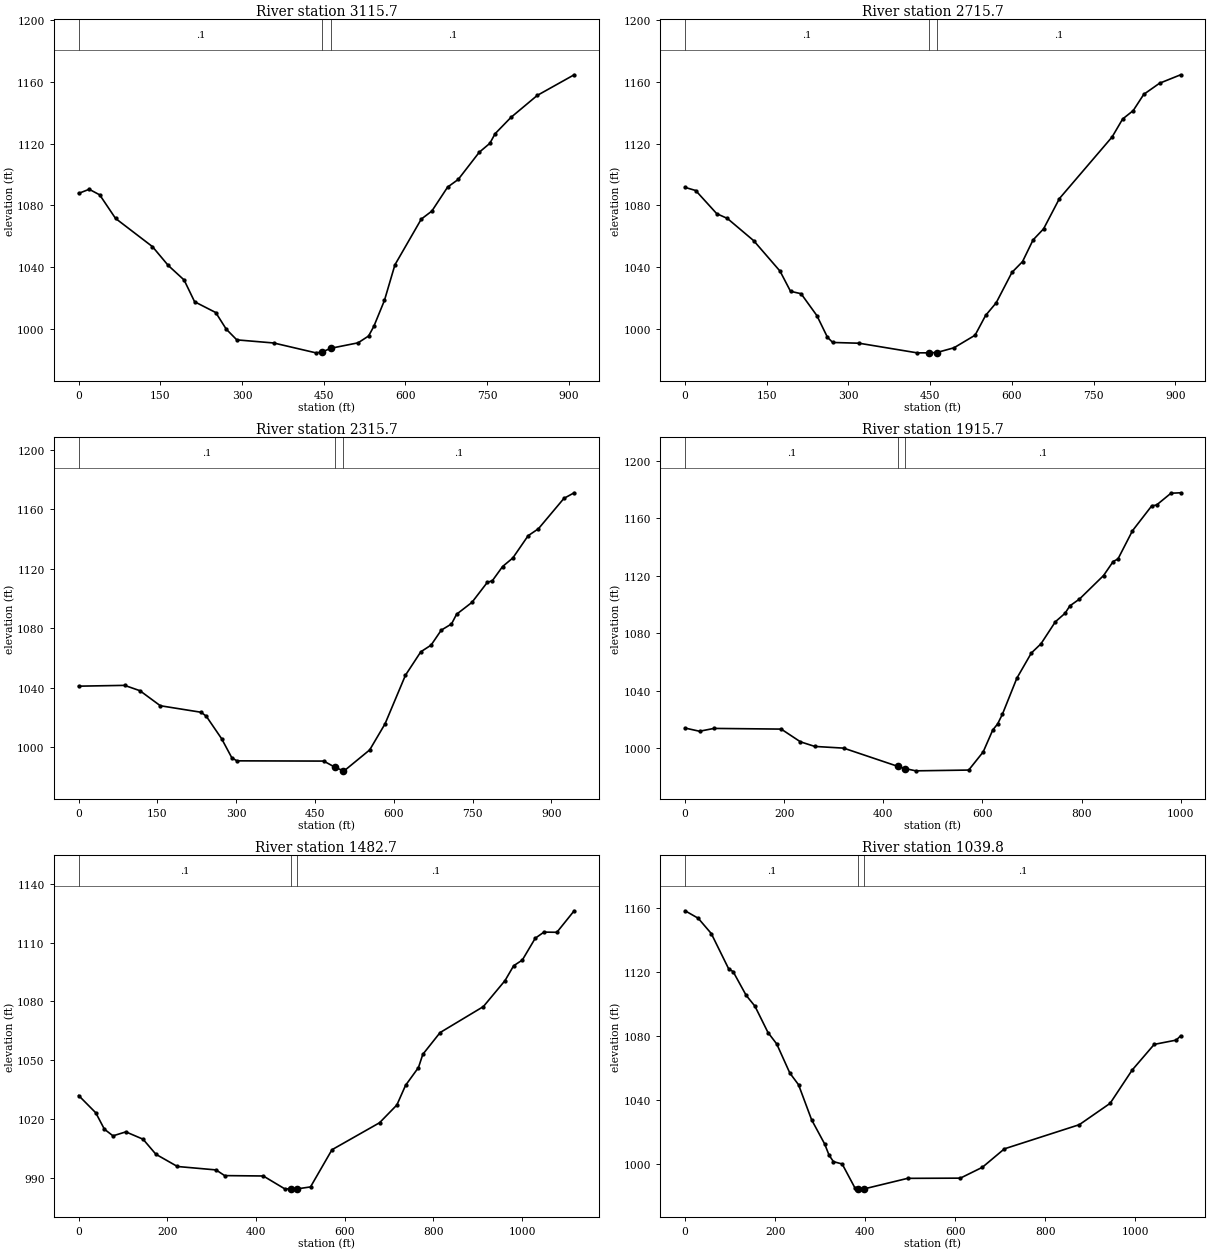
Type RM Length L Ch R = 1 ,3115.7  ,390.866,400,409.764
XS GIS Cut Line= 3
     1713819.041       348151.32     1713520.731      347807.638
     1713216.345      347469.467
#Sta/Elev= 30
       0 1087.72    19.4 1090.39    38.7 1086.77    67.8 1071.49   135.6  1053.2
   164.6 1040.99   193.7 1031.57     213 1017.46   251.8 1010.47   271.1   999.7
   290.5  992.75   358.3  990.73   435.7  984.34   447.6  984.89   462.6  987.26
   513.2  990.83   532.5  995.25   542.2 1001.53   561.6 1018.28   580.9 1041.41
   629.3 1071.05   648.7 1076.25   677.7 1091.82   697.1 1096.75   735.8 1114.41
   755.2 1120.17   764.9 1126.42   793.9 1136.97   842.3 1151.25   910.1 1164.63
#Mann= 3 , 0 , 0
       0      .1       0   447.6    .045       0   462.6      .1       0
Bank Sta=447.6,462.6
XS Rating Curve= 0 ,0
Exp/Cntr=0.3,0.1

Type RM Length L Ch R = 1 ,2715.7  ,389.789,400,401.581
XS GIS Cut Line= 3
      1714006.33      348048.107     1713867.869      347614.657
     1713733.752      347179.878
#Sta/Elev= 30
       0 1091.61    19.4  1089.6    58.1 1074.56    77.5  1071.5   125.9 1057.06
   174.3 1037.29   193.6 1024.19     213 1022.61     242 1008.42   261.4  994.36
   271.1  990.98   319.5  990.49     426  984.25   447.5  984.25   462.5  984.47
   493.8  987.53   532.5  995.69   551.8  1008.5   571.2 1016.68   600.2 1036.44
   619.6 1043.43     639 1057.52   658.3 1064.71   687.4 1084.37   784.2 1124.37
   803.5 1136.01   822.9 1141.45   842.3 1152.01   871.3 1159.21     910  1164.7
#Mann= 3 , 0 , 0
       0      .1       0   447.5    .045       0   462.5      .1       0
Bank Sta=447.5,462.5
XS Rating Curve= 0 ,0
Exp/Cntr=0.3,0.1

Type RM Length L Ch R = 1 ,2315.7  ,387.928,400,405.179
XS GIS Cut Line= 3
     1714194.108      348002.142     1714253.614      347510.084
     1714151.986      347074.225
#Sta/Elev= 30
       0 1041.17    87.5 1041.71   116.6 1038.13   155.5 1028.01   233.2 1023.62
     243 1020.95   272.1 1005.89   291.6  993.02   301.3  990.97   466.5  990.81
   488.1  986.64   503.1  984.35   505.4  984.25     554  998.32   583.2 1015.83
   622.1 1048.55   651.3 1064.28   670.8 1068.75   690.2 1078.82   709.7 1082.99
   719.4 1089.52   748.6 1097.49   777.8 1110.92   787.5 1112.08     807 1121.62
   826.4 1127.34   855.6 1142.33   875.1 1146.97   923.7 1167.41   943.2 1171.18
#Mann= 3 , 0 , 0
       0      .1       0   488.1    .045       0   503.1      .1       0
Bank Sta=488.1,503.1
XS Rating Curve= 0 ,0
Exp/Cntr=0.3,0.1

Type RM Length L Ch R = 1 ,1915.7  ,447.627,432.991,432.695
XS GIS Cut Line= 3
     1714303.947      348035.726     1714577.011      347695.543
     1714632.375      347134.736
#Sta/Elev= 30
       0 1014.03    29.1 1011.81    58.2 1013.78   193.9 1013.31   232.7 1004.46
   261.7 1001.24   319.9 1000.06   428.7  987.42   443.7  985.86   465.4  984.25
   572.2  984.79   601.4  997.41   620.8 1012.73   630.5 1016.86   640.3 1023.74
   669.4 1048.79   698.6 1066.27     718 1072.68   747.1 1088.04   766.6 1093.93
   776.3 1099.09   795.7 1103.83   844.3 1120.22   863.7 1129.96   873.4 1131.77
   902.6 1151.38   941.5 1168.73   951.2  1169.3   980.3 1177.51   999.8 1177.82
#Mann= 3 , 0 , 0
       0      .1       0   428.7    .045       0   443.7      .1       0
Bank Sta=428.7,443.7
XS Rating Curve= 0 ,0
Exp/Cntr=0.3,0.1

Type RM Length L Ch R = 1 ,1482.7  ,460.217,442.935,426.727
XS GIS Cut Line= 3
     1714786.057      348463.306     1714907.059      347904.837
      1714776.75      347374.291
#Sta/Elev= 30
       0  1031.9    38.7 1023.06    58.1  1014.7    77.5 1011.31   106.5 1013.33
   145.3 1009.59   174.3  1001.9   222.8  995.66   309.9  993.91   329.3  991.01
   416.5  990.81   464.9  984.25   478.2  984.25   493.2  984.25     523  985.23
   571.4 1004.21   678.7 1017.99   717.8 1027.06   737.3 1037.05   766.5 1046.19
   776.3 1052.92   815.3 1064.03   912.9  1077.3   961.7 1090.56   981.2 1098.15
  1000.7 1101.04  1029.9 1112.19  1049.5 1115.32  1078.7 1115.23  1117.7 1126.21
#Mann= 3 , 0 , 0
       0      .1       0   478.2    .045       0   493.2      .1       0
Bank Sta=478.2,493.2
XS Rating Curve= 0 ,0
Exp/Cntr=0.3,0.1

Type RM Length L Ch R = 1 ,1039.8  ,456.657,446.751,436.453
XS GIS Cut Line= 3
     1715437.605      348509.845     1715111.831      348100.301
     1714907.059      347560.448
#Sta/Elev= 30
       0  1158.2    29.1 1153.53    58.1 1143.98    96.9 1121.81   106.6 1120.18
   135.7 1105.27   155.1 1098.54   184.1 1082.05   203.5  1074.9   232.6 1056.71
     252 1049.37     281 1027.46   310.1 1012.27   319.8  1005.3   329.5 1001.27
   348.9  999.79   377.9  984.48   383.2  984.35   387.6  984.25   398.2  984.25
   494.2  990.81   611.4  990.94   660.3  997.73   709.2 1009.27   875.6 1024.38
   944.1 1037.75     993 1058.55    1042 1074.62  1090.9  1077.3  1100.7 1079.99
#Mann= 3 , 0 , 0
       0      .1       0   383.2    .045       0   398.2      .1       0
Bank Sta=383.2,398.2
XS Rating Curve= 0 ,0
Exp/Cntr=0.3,0.1

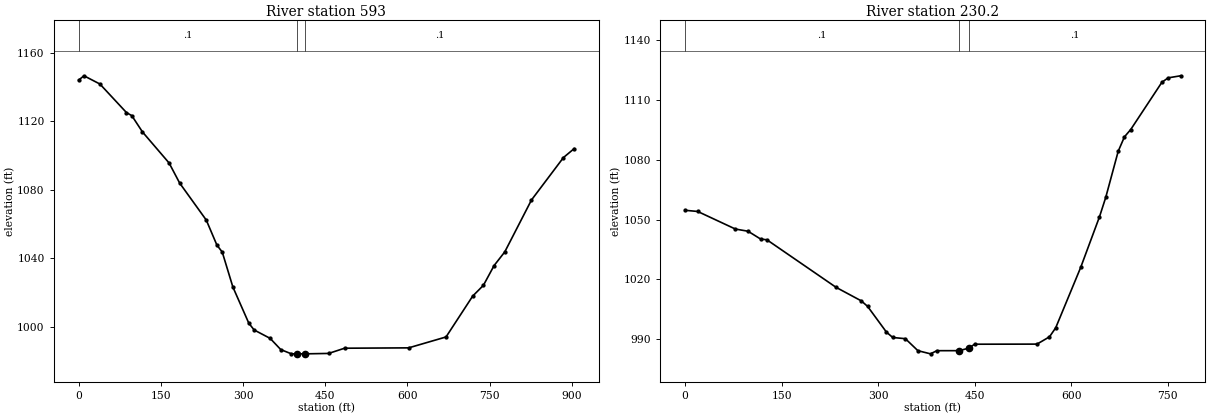
Type RM Length L Ch R = 1 ,593     ,370.071,362.886,359.078
XS GIS Cut Line= 3
     1715634.029      347942.149     1715204.909      347737.296
     1714962.906      347383.599
#Sta/Elev= 30
       0 1144.04     9.7 1146.58    38.8 1141.77    87.3 1125.09      97 1123.31
   116.5 1113.78     165 1095.68   184.4 1083.91   232.9 1062.33   252.3 1047.71
     262 1043.69   281.4 1023.27   310.5 1002.13   320.2  998.19   349.4  993.28
   368.8  986.73   388.2  984.25   398.9  984.25   413.9  984.25   456.1  984.49
   485.2  987.53   602.1  987.74   670.3   994.1     719 1017.98   738.5 1024.25
     758 1035.79   777.5 1043.77   826.2 1074.07   884.6 1098.86   904.1 1104.05
#Mann= 3 , 0 , 0
       0      .1       0   398.9    .045       0   413.9      .1       0
Bank Sta=398.9,413.9
XS Rating Curve= 0 ,0
Exp/Cntr=0.3,0.1

Type RM Length L Ch R = 1 ,230.2   ,230.317,230.162,226.63
XS GIS Cut Line= 3
     1715696.501      347467.789     1715251.448      347402.215
     1714990.829      347216.058
#Sta/Elev= 30
       0 1054.67    19.6 1054.08    78.2 1045.26    97.8 1044.17   117.4 1040.24
   127.1 1039.88   234.7 1016.01   273.8 1009.24   283.6 1006.48   312.9  993.56
   322.7  990.87   342.3  990.27   361.8  984.25   381.4  982.67   391.2  984.25
     426  984.26     441  985.54   449.9   987.5   546.9  987.55   566.3  991.21
     576  995.76   614.8 1026.03     644 1051.42   653.7 1061.13   673.1  1084.3
   682.8 1091.53   692.5 1095.17     741 1118.89   750.7  1121.1   770.1 1122.14
#Mann= 3 , 0 , 0
       0      .1       0     426    .045       0     441      .1       0
Bank Sta=426,441
XS Rating Curve= 0 ,0
Exp/Cntr=0.3,0.1

Chan Stop Cuts=-1
Use User Specified Reach Order=0